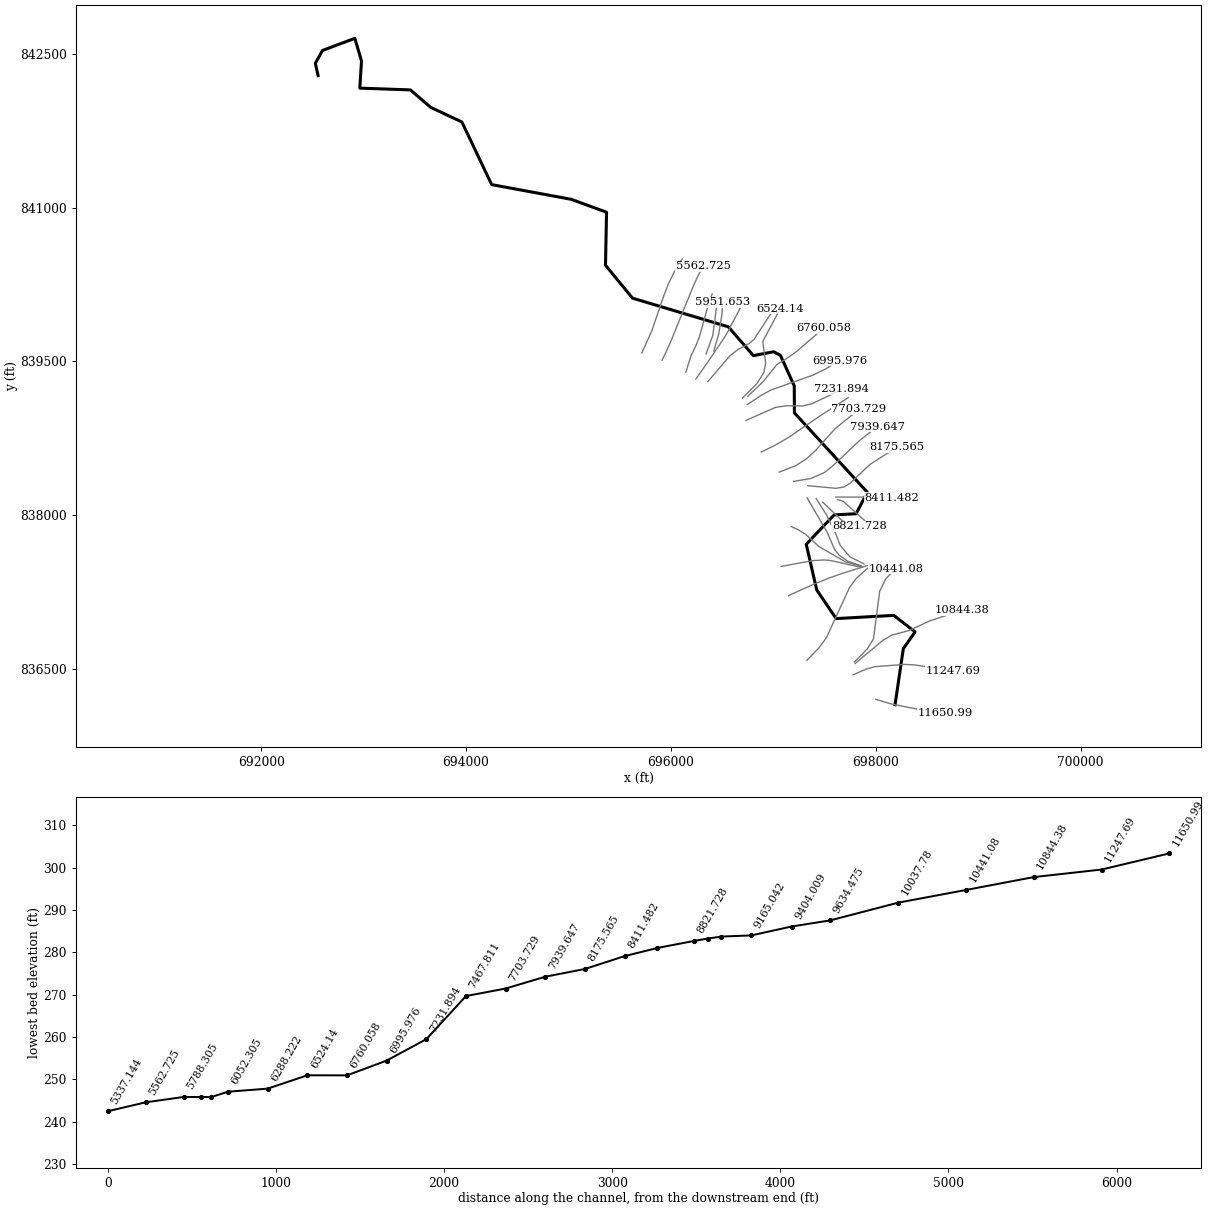
--- 13386_ras.prj (project) ---

Proj Title=13386
Current Plan=p01
Default Exp/Contr=0.3,0.1
English Units
Geom File=g01
Flow File=f01
Plan File=p01
Y Axis Title=Elevation
X Axis Title(PF)=Main Channel Distance
X Axis Title(XS)=Station
BEGIN DESCRIPTION:
RFD model 13386 exported to HEC-RAS
END DESCRIPTION:

--- 13386_ras.p01 (plan) ---

Plan Title=Plan 01
Program Version=4.10
Short Identifier=Plan 01
Geom File=g01
Flow File=f01
Subcritical Flow
Calc Critical at every XS
Secant Critical Depth

--- 13386_ras.f01 (steady flow) ---

Flow Title=Flow 01
Program Version=5.01
Number of Profiles= 6
Profile Names=10yr,25yr,50yr,100yr,100plus,500yr
River Rch & RM=13386,35,11650.99
 2048.44 3377.64 4660.35 5857.58 8552.0710700.37
River Rch & RM=13386,35,11247.69
 2102.12 3472.47 4797.02 6035.83 8812.3211005.47
River Rch & RM=13386,35,10844.38
  546.15  910.94 1264.87 1602.43 2339.54 3583.69
River Rch & RM=13386,35,10441.08
 2438.14 4042.84 5599.53  7060.810308.7712651.03
River Rch & RM=13386,35,10037.78
 2442.46  4050.4 5610.38 7074.8910329.3412674.34
River Rch & RM=13386,35,9634.475
 2448.61 4061.21 5625.92  7095.110358.8512707.87
River Rch & RM=13386,35,9404.009
 2479.31 4115.51 5704.25 7197.3710508.1512878.73
River Rch & RM=13386,35,9165.042
 2481.14 4118.75 5708.93 7203.4710517.0712888.92
River Rch & RM=13386,35,8986.935
 2502.34 4156.11 5762.72 7273.5810619.4213005.38
River Rch & RM=13386,35,8821.728
 2503.18 4157.59 5764.85 7276.3610623.4813009.99
River Rch & RM=13386,35,8606.438
 2504.86 4160.55 5769.12 7281.91 10631.613019.21
River Rch & RM=13386,35,8411.482
 2507.55 4165.29 5775.94  7290.810644.5713033.96
River Rch & RM=13386,35,8175.565
 2514.78 4178.03 5794.28  7314.710679.4613073.58
River Rch & RM=13386,35,7939.647
 2566.14 4267.76 5922.82 7481.4810922.9713346.84
River Rch & RM=13386,35,7703.729
 2568.13 4271.27 5927.88 7488.0910932.61 13357.8
River Rch & RM=13386,35,7467.811
 2611.29 4347.16    6037 7630.14   1114013591.63
River Rch & RM=13386,35,7231.894
 2613.86 4351.73 6043.63 7638.8311152.6913606.14
River Rch & RM=13386,35,6995.976
 2615.62 4354.86 6048.18 7644.7911161.3913616.11
River Rch & RM=13386,35,6760.058
 2629.63  4379.7 6084.07  7691.711229.8913693.95
River Rch & RM=13386,35, 6524.14
 2636.04 4391.12 6100.61 7713.3911261.5513730.09
River Rch & RM=13386,35,6288.222
 2641.59 4401.03    6115 7732.2711289.1213761.69
River Rch & RM=13386,35,6052.305
 2642.86 4403.29 6118.29 7736.5911295.4213768.91
River Rch & RM=13386,35,5951.653
  2722.3 4543.18 6319.66 7998.9911678.5214199.33
River Rch & RM=13386,35,5893.229
 2722.93 4544.31  6321.3 8001.1311681.6514202.89
River Rch & RM=13386,35,5788.305
 2743.08 4580.19 6373.31  8069.311781.1814315.91
River Rch & RM=13386,35,5562.725
 2744.81 4583.28 6377.79 8075.1811789.7714325.68
River Rch & RM=13386,35,5337.144
 2756.05 4603.39 6407.01 8113.5711845.8114389.58
River Rch & RM=13386,35,5111.564
 2756.36 4603.94 6407.82 8114.6311847.3614391.35
Boundary for River Rch & Prof#=13386,35,1
Up Type= 0
Dn Type= 2
Boundary for River Rch & Prof#=13386,35,2
Up Type= 0
Dn Type= 2
Boundary for River Rch & Prof#=13386,35,2
Up Type= 0
Dn Type= 2
Boundary for River Rch & Prof#=13386,35,2
Up Type= 0
Dn Type= 2
Boundary for River Rch & Prof#=13386,35,2
Up Type= 0
Dn Type= 2
Boundary for River Rch & Prof#=13386,35,2
Up Type= 0
Dn Type= 2

--- 13386_ras.g01 (geometry) ---

Geom Title=13386
Program Version=4.10

River Reach=13386,35
Reach XY= 30
698188.488735765836146.904747918698269.217902452836693.779747903
698383.801235795836857.842247903698176.504398346837019.259961724
697613.286832392836987.621434376697423.572910517 837267.82472457
697321.472825646837712.948969737697593.885381669838000.459307656
697808.262079537  838011.2680296697917.744681835838221.169842005
697205.732378781838996.383745745697204.464213789839258.976526156
697070.476183265839556.369342059697004.055752188839592.959302321
 696804.84687829839555.456066713696560.816644967 839836.44115518
695624.379062682840116.556090564695361.435431182840438.041841686
 695371.56893608840955.233811498695027.177525699841081.165446386
694250.060575306841224.963112488 693959.52809003841836.271913022
693656.517526746841977.958342627693456.435162395842149.548927158
692962.837580651842166.922940582692979.181928426842432.380678773
692913.893450618842653.041376248692598.273622334842534.651977554
692528.536593229842409.476061568692555.379055202842289.412530467

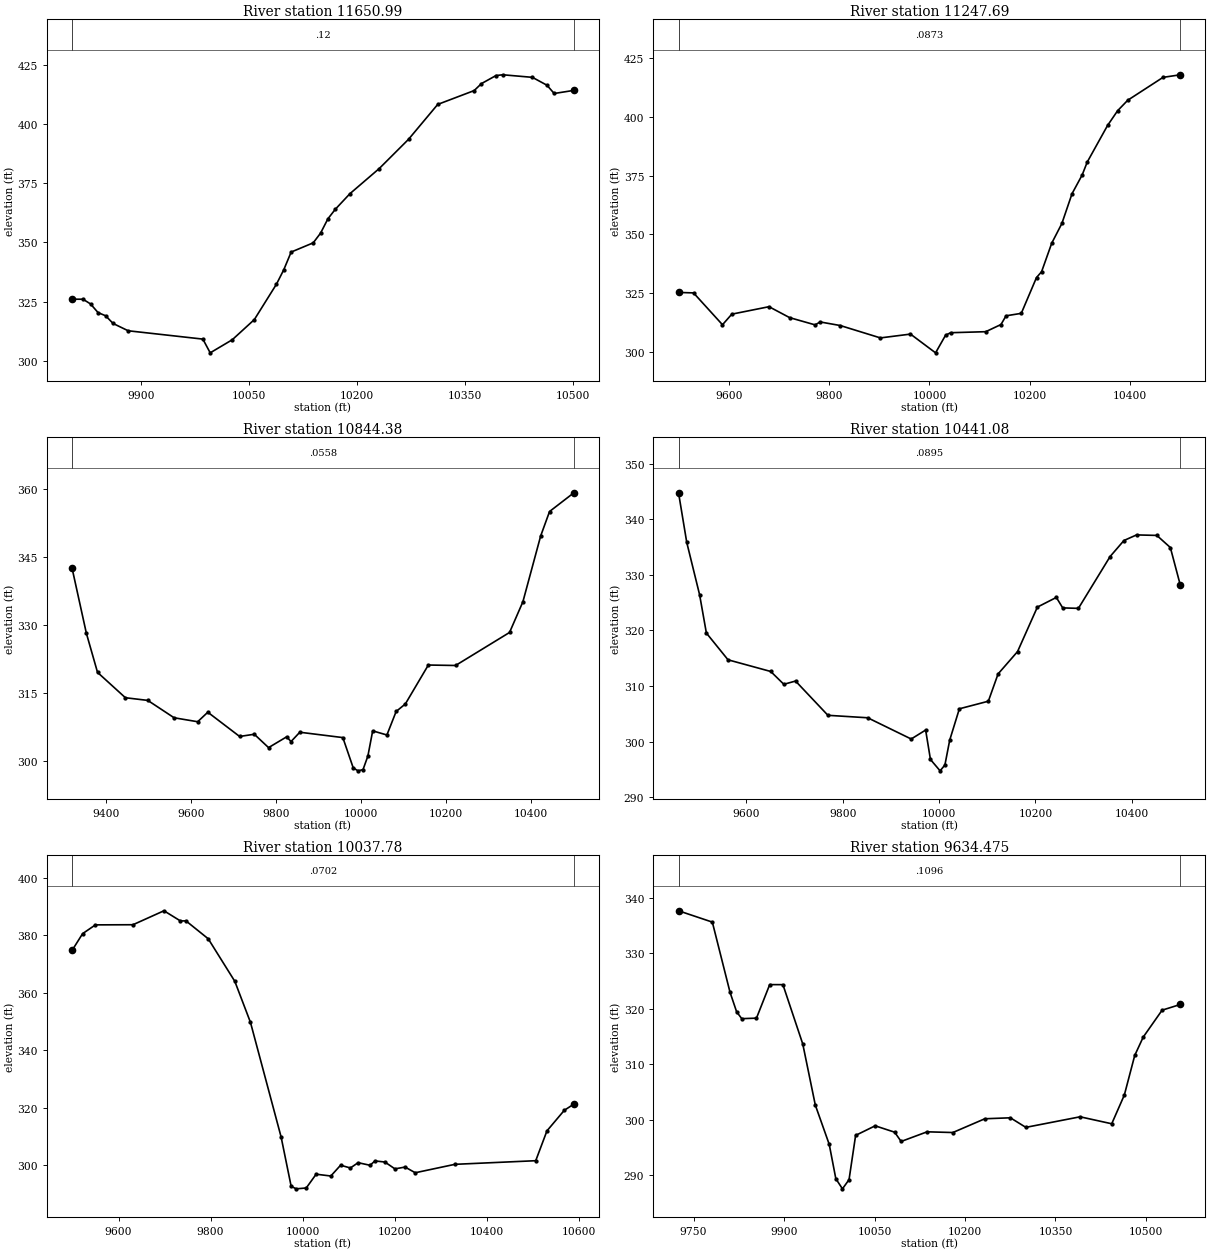
Type RM Length L Ch R = 1 ,11650.99,403.303000,403.303000,403.303000
XS GIS Cut Line= 6
698000.479361862836199.727020532698147.254245311836155.332148373
698352.834367752836113.662024617 698470.37024343836092.510467783
698587.890560746836074.446090326698682.077424854836062.285439596
#Sta/Elev= 30
9804.574326.03579819.745 326.0119830.192324.0227 9840.64320.37039851.087319.0397
9861.534315.77669882.429 312.7019986.101309.18329996.266303.387510026.89308.9087
10057.54317.425110088.18332.3362 10098.4338.457610108.61345.913210139.26349.8104
10149.47353.913710159.69359.977510169.89363.966710190.21370.558410230.86381.1595
 10271.5393.492710312.03408.225610362.62 414.06510372.74 417.01510392.97420.4138
10402.37420.734910443.43419.6533 10463.6416.335910473.68412.837610500.98414.1498
#Mann= 3 , 0 , 0
9804.574    0.12       09804.574    0.12       010500.98    0.12       0
#XS Ineff= 2 , 0
       09809.409                       0
Bank Sta=9804.574,10500.98
Exp/Cntr=0.3,0.1

Type RM Length L Ch R = 1 ,11247.69,403.302900,403.302900,403.302900
XS GIS Cut Line= 6
697778.029286014836438.404181243697903.446365015836493.596768769
697990.244745463 836518.05867884698280.914534922836540.472814128
698375.738850621836535.846306218 698759.31502868836479.990736135
#Sta/Elev= 30
9499.065325.28179529.014 325.082 9586.82311.52929605.446316.03699679.697319.2102
9720.975314.54899771.764311.47589781.834312.71819822.011311.19349902.114 305.926
9962.191307.549910012.26 299.57210032.27307.083510042.27308.137610112.47308.5717
10142.86311.628810152.99315.336310183.39316.378410213.79331.623510223.92 334.097
10244.19 346.24210264.45354.634110284.72367.304210304.98375.289210315.11380.7858
10355.64396.343110375.81402.647410395.94407.0843 10466.4416.822710500.94417.9234
#Mann= 3 , 0 , 0
9499.065  0.0873       09499.065  0.0873       010500.94  0.0873       0
#XS Ineff= 2 , 0
       0                               0
Bank Sta=9499.065,10500.94
Exp/Cntr=0.3,0.1

Type RM Length L Ch R = 1 ,10844.38,403.303000,403.303000,403.303000
XS GIS Cut Line= 6
697799.324390024836549.896487534698066.716620535836772.757342413
698156.397481441836826.240684256698321.569212586 836869.88897714
698532.758138031836967.413269565698839.666733712837067.717921361
#Sta/Elev= 30
9321.052342.51219354.706328.13839380.921319.51579446.457313.9229  9499.1313.3324
9560.974309.49999616.401308.62359640.213310.7227 9715.02305.37429749.557305.8619
9783.079 302.9139825.578305.29239835.959304.25059856.506306.30789957.731305.1268
9982.181298.43639993.582297.7883 10005.2298.060810016.64301.0593 10027.9 306.612
10061.35305.700410083.06310.887710104.69312.544110158.78321.139910222.76321.0373
10349.73328.327110381.09335.0941 10422.9349.6185 10443.8355.017910500.95 359.152
#Mann= 3 , 0 , 0
9321.052  0.0558       09321.052  0.0558       010500.95  0.0558       0
#XS Ineff= 2 , 0
       0                10063.86       0
Bank Sta=9321.052,10500.95
Exp/Cntr=0.3,0.1

Type RM Length L Ch R = 1 ,10441.08,403.303000,403.303000,403.303000
XS GIS Cut Line= 6
 697792.44671908836565.371247157697916.676395595836691.147438481
697977.830289543836788.251623452698038.426274806837254.755279928
698098.187018543837376.893809915698195.683698893837476.457656235
#Sta/Elev= 30
9459.178344.74089476.234335.81799502.946326.38899516.994319.51759561.902314.7071
9650.598312.60739677.778310.30249702.087310.88899769.311304.7266 9851.91304.2833
9942.175300.46649972.176302.07559982.176296.784410002.18294.741910012.18295.7924
10022.18300.278610042.19 305.89810102.35307.261710122.55 312.16910162.96316.1824
10204.13324.1828 10243.5325.923810256.76324.039310289.33323.959610355.15 333.279
10383.87336.159510410.04337.164510452.13337.0745 10480.2334.895710500.91328.1272
#Mann= 3 , 0 , 0
9459.178  0.0895       09459.178  0.0895       010500.91  0.0895       0
#XS Ineff= 2 , 0
       0                               0
Bank Sta=9459.178,10500.91
Exp/Cntr=0.3,0.1

Type RM Length L Ch R = 1 ,10037.78,403.303000,403.303000,403.303000
XS GIS Cut Line= 6
697328.524168968 836581.15069744697444.260928065836700.222446918
697518.949415743836802.261482209697744.035693645837290.903642103
 697808.66356495837378.773485526 697919.68363151837478.382064477
#Sta/Elev= 30
9499.087374.78379522.012380.6273 9549.84383.68419631.426383.7318 9698.76388.5919
9734.425385.06369746.557 385.072 9794.93378.83899852.715364.01579886.738 349.705
9953.267309.8161 9975.09292.64299986.002291.742910007.89292.040110029.39296.8403
10061.28 296.21110082.54299.966310103.81299.010810120.58300.850910146.52299.9501
10157.26301.463310178.73301.083110200.58298.700510222.67299.324810244.75297.3464
10330.85300.278410506.51301.542110530.93311.944110568.59319.097110589.36321.2568
#Mann= 3 , 0 , 0
9499.087  0.0702       09499.087  0.0702       010589.36  0.0702       0
#XS Ineff= 2 , 0
       0                10386.98       0
Bank Sta=9499.087,10589.36
Exp/Cntr=0.3,0.1

Type RM Length L Ch R = 1 ,9634.475,230.466000,230.466000,230.466000
XS GIS Cut Line= 6
697147.694498609837210.842071463697189.763772608837231.179598912
697398.811146284 837325.15392283 697541.43011692837382.936219179
697679.216895438837431.202543912697923.905980454837506.803852557
#Sta/Elev= 30
9725.074337.61289781.119335.57139810.434322.94379821.398319.4218  9829.9318.1932
 9854.29318.28649876.217324.32159898.145324.31599931.037313.6351 9951.85 302.635
9974.893295.57289985.856289.3836 9996.82287.561710007.75289.213210018.66297.1841
10051.06298.906610083.36297.758410094.13 296.089 10137.2297.827210179.86297.6973
10232.84300.174710275.23300.348910300.89298.626610390.84300.528410443.26299.2741
10464.14304.437110481.38311.565510495.47314.876410526.81319.723310556.99320.7478
#Mann= 3 , 0 , 0
9725.074  0.1096       09725.074  0.1096       010556.99  0.1096       0
#XS Ineff= 2 , 0
       0                10246.54       0
Bank Sta=9725.074,10556.99
Exp/Cntr=0.3,0.1

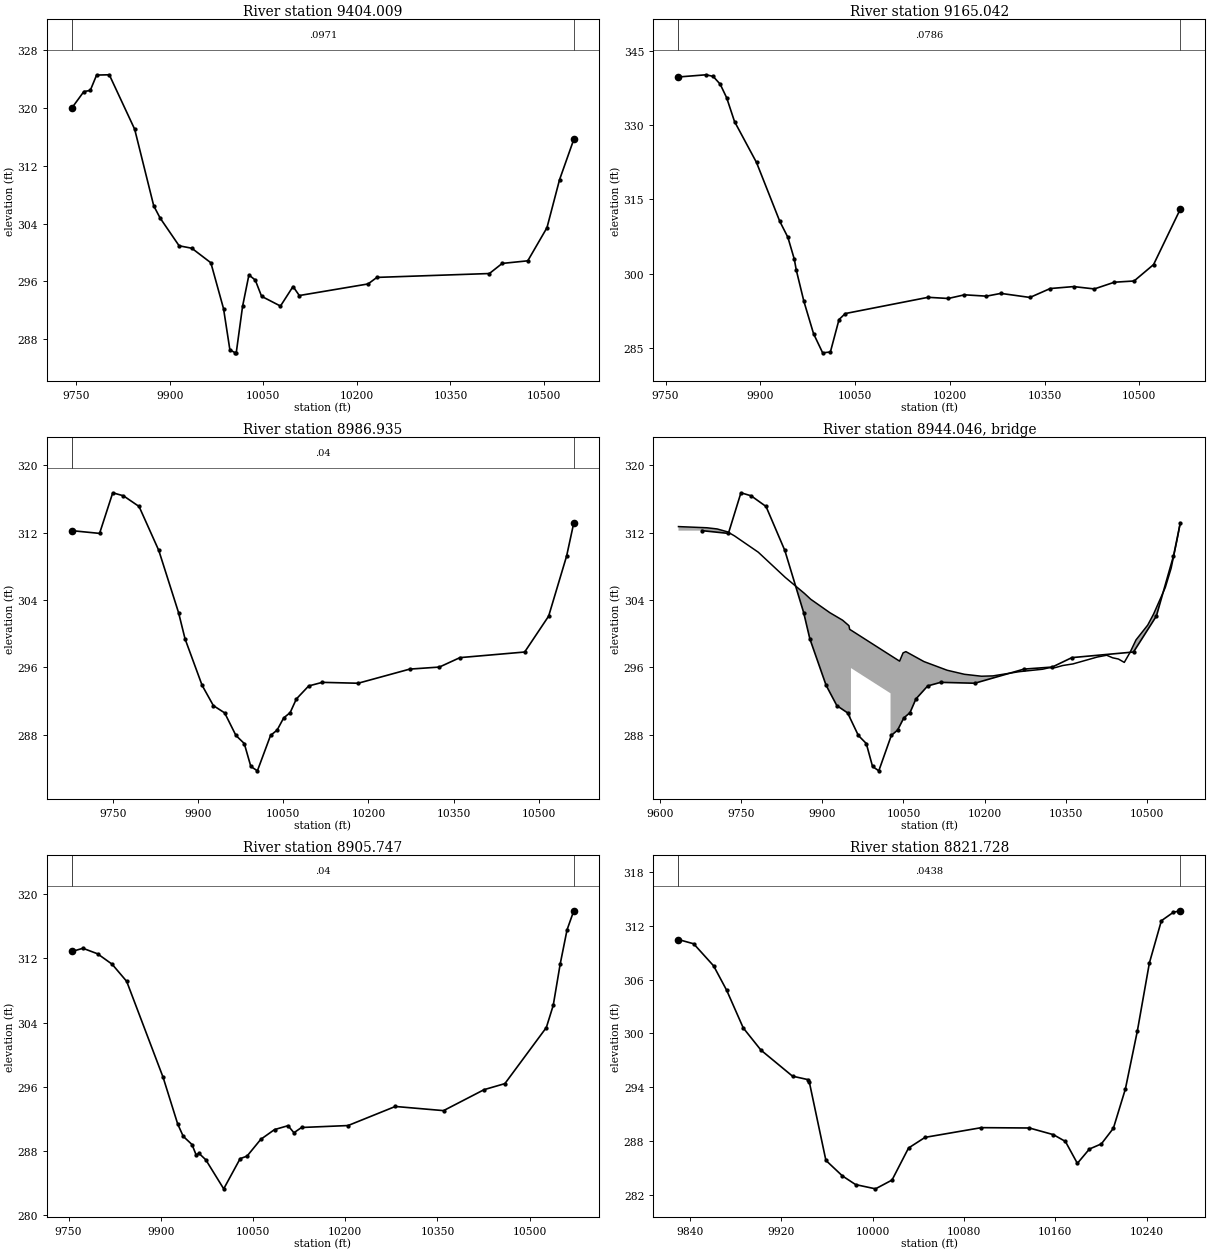
Type RM Length L Ch R = 1 ,9404.009,238.967000,238.967000,238.967000
XS GIS Cut Line= 6
697076.160450041837496.720623642697381.158310741837553.560796306
697500.982830405837560.344487071697556.799710959837555.513373584
697829.731823146837493.879842222697867.831138223837495.996470839
#Sta/Elev= 30
9743.283320.02559762.452322.28659772.626 322.431  9782.8324.56359803.149324.6029
9843.847317.0598 9874.37306.46229884.544304.78149915.068300.92869935.416300.5896
9965.939298.57819986.288292.21989996.463286.520210005.16286.108810006.64286.1097
 10016.8292.548210026.96296.893510037.12296.185710047.28293.933610077.53292.5843
10097.67295.292510107.73294.042710217.91295.645310232.09296.552410412.44297.0883
10432.95298.486810473.95298.848110504.71303.431310524.85310.069110547.72315.6558
#Mann= 3 , 0 , 0
9743.283  0.0971       09743.283  0.0971       010547.72  0.0971       0
#XS Ineff= 2 , 0
       0                10206.07       0
Bank Sta=9743.283,10547.72
Exp/Cntr=0.3,0.1

Type RM Length L Ch R = 1 ,9165.042,178.107800,178.107800,178.107800
XS GIS Cut Line= 6
697174.639128834837885.987841308697244.352610588837854.971651539
697319.554570585837806.501675233697444.187869102837691.813405693
697703.439649105837541.856757492697856.542452276837499.524185196
#Sta/Elev= 30
9770.474339.73719814.239340.18139825.344339.85559836.449338.2926 9846.77335.5348
9859.162330.74289893.984322.47079930.806310.58029943.638307.35549953.842302.9194
9956.937300.73279969.011294.4066 9984.32287.8686  9998.7284.013310010.94284.1853
10024.61 290.73810034.49291.948510165.64295.2298 10197.5294.994710223.21295.7334
10258.03295.463910280.77296.020810326.83295.202710358.92297.002110395.91297.3967
10428.78296.922410460.47298.280210491.67298.526210522.53301.843410564.86313.0521
#Mann= 3 , 0 , 0
9770.474  0.0786       09770.474  0.0786       010564.86  0.0786       0
#XS Ineff= 2 , 0
       0                10178.15       0
Bank Sta=9770.474,10564.86
Exp/Cntr=0.3,0.1

Type RM Length L Ch R = 1 ,8986.935,81.187900,81.187900,81.187900
XS GIS Cut Line= 6
697329.184829265838166.999451563697521.893162578837837.138340458
697600.018162578 837660.05500713697645.157051444837604.499451578
697728.490384817837547.207784891697856.962606996 837503.80500713
#Sta/Elev= 30
9677.759312.23499726.436311.91129749.615316.73179768.394316.37319795.975315.1067
9830.744 309.8829865.513302.51349876.959299.39669907.003293.88059926.873291.4698
9946.742290.60839966.612287.92899981.255286.97469992.827284.2521 10004.4283.7309
10027.54287.930110039.12288.565410050.69290.010510062.11290.641110072.98292.2566
10094.72293.804810118.72294.232910181.78294.127310272.76295.805110324.94296.0472
10361.16297.167110475.16297.833510517.38 302.09410549.05309.228210561.68313.1675
#Mann= 3 , 0 , 0
9677.759    0.04       09677.759    0.04       010561.68    0.04       0
#XS Ineff= 2 , 0
       09940.122        10046.69       0
Bank Sta=9677.759,10561.68
Exp/Cntr=0.3,0.1

Type RM Length L Ch R = 3 ,8944.046,,,
BEGIN DESCRIPTION:
END DESCRIPTION:
Bridge Culvert--1,0,-1,-1, 0
Deck Dist Width WeirC Skew NumUp NumDn MinLoCord MaxHiCord MaxSubmerge Is_Ogee
31.243950,18.700000,2.6,0, 44, 44, , , 0.95, 0, 0,0,,
 9634.16 9686.54 9705.56 9724.57 9737.60 9781.61 9831.66 9866.93 9878.69 9913.96
 9937.48 9949.21 9950.59 9952.95 9952.9510026.1110026.1110042.8210049.2510054.47
10087.8110130.7510162.6310194.2510215.3610263.8310307.1010318.7510330.9810344.30
10363.2210408.3310425.6210436.4510447.2710458.1010468.9310479.7610501.4210512.25
10533.9110544.7410555.5710561.45
  312.72  312.58  312.44  312.10  311.62  309.68  306.68  304.79  304.09  302.50
  301.61  300.96  300.52  300.43  300.43  297.43  297.43  296.75  297.73  297.88
  296.70  295.67  295.19  294.96  295.00  295.50  295.79  295.96  295.99  296.23
  296.42  297.24  297.45  297.15  297.00  296.60  297.81  299.27  301.03  302.34
  305.49  307.78  311.13  313.13
 -687.28 -687.42 -687.56 -687.90 -688.38 -690.32 -693.32 -695.21 -695.91 -697.50
 -698.39 -699.04 -699.48 -699.57  295.93  292.93 -702.57 -703.25 -702.27 -702.12
 -703.30 -704.33 -704.81 -705.04 -705.00 -704.50 -704.21 -704.04 -704.01 -703.77
 -703.58 -702.76 -702.55 -702.85 -703.00 -703.40 -702.19 -700.73 -698.97 -697.66
 -694.51 -692.22 -688.87 -686.87
 9634.16 9686.54 9705.56 9724.57 9737.60 9781.61 9831.66 9866.93 9878.69 9913.96
 9937.48 9949.21 9950.59 9967.09 9967.0910040.2510040.2510042.8210049.2510054.47
10087.8110130.7510162.6310194.2510215.3610263.8310307.1010318.7510330.9810344.30
10363.2210408.3310425.6210436.4510447.2710458.1010468.9310479.7610501.4210512.25
10533.9110544.7410555.5710561.45
  312.72  312.58  312.44  312.10  311.62  309.68  306.68  304.79  304.09  302.50
  301.61  300.96  300.52  299.85  299.85  296.85  296.85  296.75  297.73  297.88
  296.70  295.67  295.19  294.96  295.00  295.50  295.79  295.96  295.99  296.23
  296.42  297.24  297.45  297.15  297.00  296.60  297.81  299.27  301.03  302.34
  305.49  307.78  311.13  313.13
 -687.28 -687.42 -687.56 -687.90 -688.38 -690.32 -693.32 -695.21 -695.91 -697.50
 -698.39 -699.04 -699.48 -700.15  295.35  292.35 -703.15 -703.25 -702.27 -702.12
 -703.30 -704.33 -704.81 -705.04 -705.00 -704.50 -704.21 -704.04 -704.01 -703.77
 -703.58 -702.76 -702.55 -702.85 -703.00 -703.40 -702.19 -700.73 -698.97 -697.66
 -694.51 -692.22 -688.87 -686.87
BR Coef=-1 , 0 , 0 ,, 0 ,,,0.8,0,1,0,
WSPro=,,,, 1 ,,,, 0 ,,,, 0 ,,,,-1 ,-1 ,-1 , 0 , 0 , 0 , 0 , 0
BC Design=,, 0 ,, 0 ,,,,,,

Type RM Length L Ch R = 1 ,8905.747,84.019200,84.019200,84.019200
XS GIS Cut Line= 6
697417.726495922838160.055007115 697518.42094034838002.068895996
697606.962607026837819.777229339697653.837606996837701.721673787
697745.851495922837592.346673772697884.740384817837521.166118219
#Sta/Elev= 30
9755.586312.86739773.439 313.2689797.156312.58419820.872311.28419844.589309.1443
9903.882297.15929927.599291.34149936.568289.81569950.836288.79169957.644287.4713
9962.017287.70459973.197286.895810002.37283.2684 10029.1 287.03510040.28287.3477
10062.64289.4423   10085290.657610106.97291.143910116.56290.263610128.92290.9185
10204.56291.161810281.43293.540910359.84293.022110425.86295.640110459.57296.3902
10526.99303.384510538.22306.156210549.46311.2794 10560.7315.577210571.64317.9455
#Mann= 3 , 0 , 0
9755.586    0.04       09755.586    0.04       010571.64    0.04       0
#XS Ineff= 2 , 0
       09957.984        10059.67       0
Bank Sta=9755.586,10571.64
Exp/Cntr=0.3,0.1

Type RM Length L Ch R = 1 ,8821.728,215.289200,215.289200,215.289200
XS GIS Cut Line= 3
697482.717968285838124.186249956697673.690190524 837941.89458327
697840.790884972837887.641111046
#Sta/Elev= 30
9829.917310.45969843.222309.98829860.721307.52729872.187304.7965 9886.67300.6127
9902.194298.13959929.843295.23789943.668294.84619944.601294.55769959.084285.8549
9973.566284.12169985.141 283.15810002.53282.685210017.01283.6631 10031.5287.2354
10045.98288.4213 10095.3289.502410137.36289.464710158.39288.7223 10168.9287.9678
10179.41285.521510189.93287.117810200.44287.695510210.96289.436410221.47293.8085
10231.98300.2822 10242.5307.848210253.01312.555710263.53313.500410269.61313.6658
#Mann= 3 , 0 , 0
9829.917  0.0438       09829.917  0.0438       010269.61  0.0438       0
#XS Ineff= 2 , 0
       09971.863         10124.1       0
Bank Sta=9829.917,10269.61
Exp/Cntr=0.3,0.1

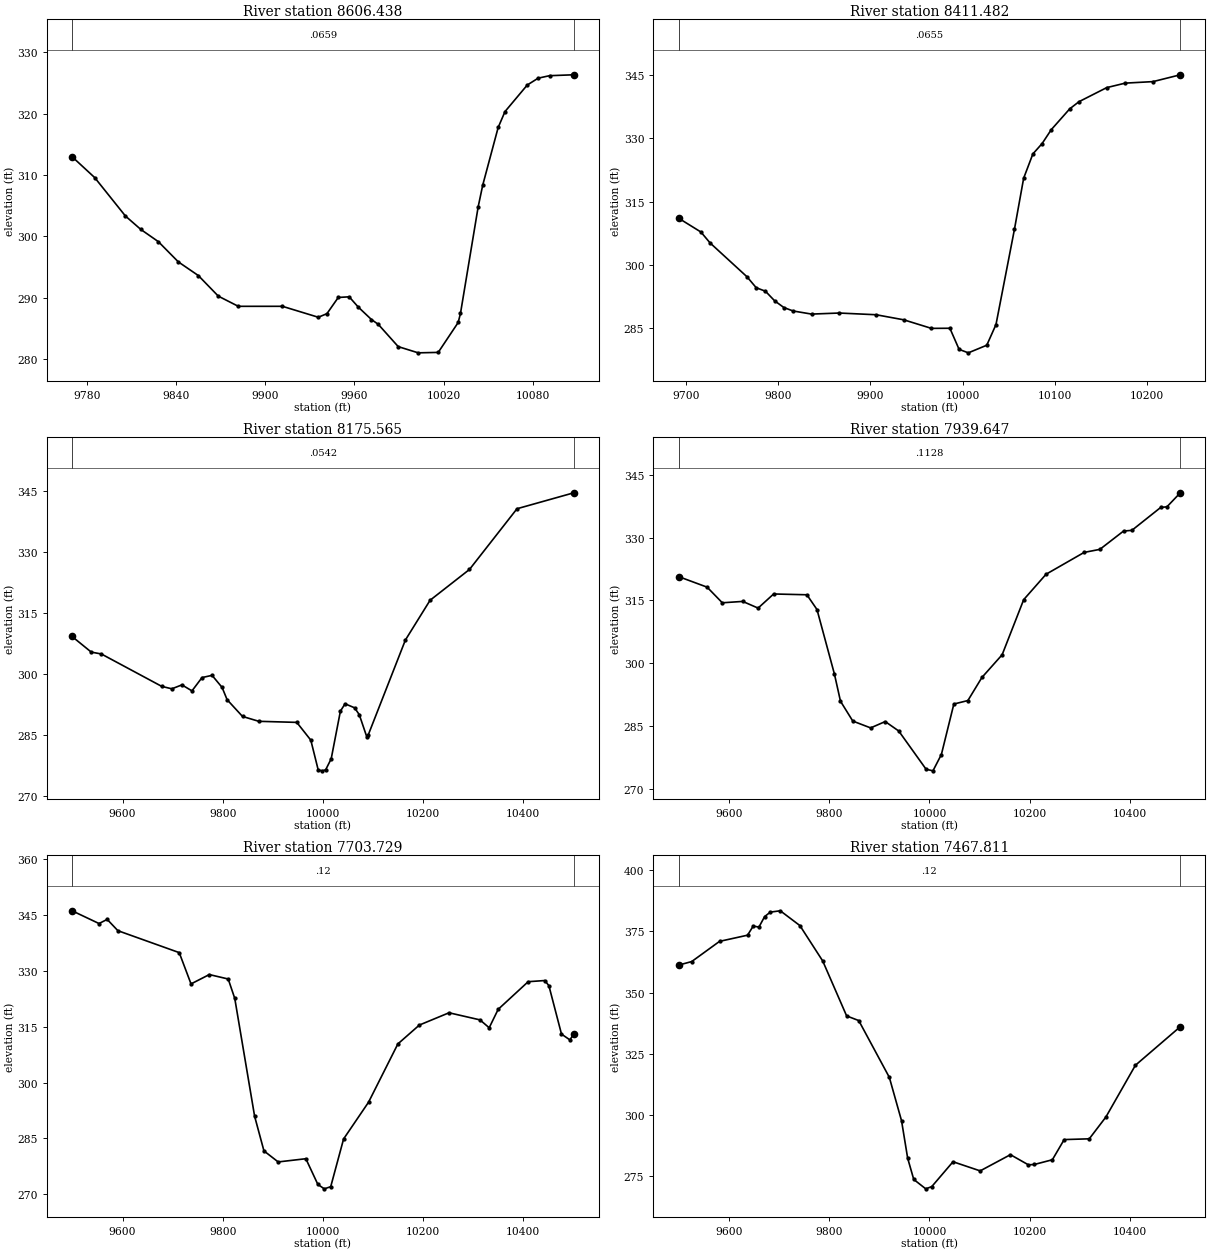
Type RM Length L Ch R = 1 ,8606.438,194.956000,194.956000,194.956000
XS GIS Cut Line= 3
697630.287412733838148.057777733697680.200607181838135.036944404
697892.874218315837944.064722165
#Sta/Elev= 30
9770.177312.97399785.382309.57539806.052 303.3199816.386 301.1369828.211299.1412
9841.651295.84719855.091293.62469868.531 290.2729881.971288.6175 9911.62288.6195
9935.731286.83899941.554287.42029949.171  290.069956.521290.16559962.611 288.497
9971.489286.46719976.051285.69059989.491282.056510002.93 281.04510016.39281.1168
10029.81285.987810031.36287.478110043.25304.820110046.32308.351210056.69317.7309
10061.29320.321210076.26324.643510083.57325.755810091.23326.161410107.59326.3099
#Mann= 3 , 0 , 0
9770.177  0.0659       09770.177  0.0659       010107.59  0.0659       0
#XS Ineff= 2 , 0
       0                               0
Bank Sta=9770.177,10107.59
Exp/Cntr=0.3,0.1

Type RM Length L Ch R = 1 ,8411.482,235.917800,235.917800,235.917800
XS GIS Cut Line= 3
697610.756162736838174.099444404698059.974912733838174.099444404
698154.508703855838165.575905851
#Sta/Elev= 30
9692.067311.0587 9716.31307.7753 9726.31305.1736 9766.31297.1555 9776.31294.5596
 9786.31293.7324 9796.31291.4534 9806.31289.8602 9816.31289.0467 9836.31288.3113
 9866.31288.5609 9906.31288.1551 9936.31286.9528 9966.31284.9227 9986.31284.9515
 9996.31279.944610006.31279.122110026.31280.928410036.31285.831710056.31308.3992
10066.31320.530510076.31326.288110086.31328.743310096.31332.056310116.31336.9854
10126.31338.673610156.37342.009210176.45343.074510206.57343.4331 10236.2345.0545
#Mann= 3 , 0 , 0
9692.067  0.0655       09692.067  0.0655       0 10236.2  0.0655       0
#XS Ineff= 2 , 0
       0                               0
Bank Sta=9692.067,10236.2
Exp/Cntr=0.3,0.1

Type RM Length L Ch R = 1 ,8175.565,235.917700,235.917700,235.917700
XS GIS Cut Line= 6
697336.739647176838285.238599263697610.162104596838259.910820075
697693.773523552838273.598533658697750.540395553838310.744045129
697945.307309745838493.952364153698202.670796029838658.945497175
#Sta/Elev= 30
9499.162309.14899537.519305.3019 9557.57304.84979678.192296.86789698.325296.2715
9718.457297.23539738.547295.75939758.607299.03879778.657299.58339798.674296.6113
9808.683293.59459839.422289.46899871.982288.26919947.817288.00479975.823283.6255
9990.616276.2725    9999276.076210005.41276.324210016.52279.045510034.88290.7774
10044.18292.5784 10063.1291.598310072.53 289.91710087.43  284.4910090.48284.9223
10164.66308.287810213.93318.070510292.58325.652510387.46340.599410500.97344.5284
#Mann= 3 , 0 , 0
9499.162  0.0542       09499.162  0.0542       010500.97  0.0542       0
#XS Ineff= 2 , 0
       0                10049.74       0
Bank Sta=9499.162,10500.97
Exp/Cntr=0.3,0.1

Type RM Length L Ch R = 1 ,7939.647,235.917800,235.917800,235.917800
XS GIS Cut Line= 6
 697198.46501093838326.968467788697365.971919852838355.767013817
697497.162986379  838412.8663325697581.300430178838479.175108431
697841.479627251 838725.53816638698016.346823797838863.151680136
#Sta/Elev= 30
9499.088320.70269556.185318.17259586.484314.43599627.237314.76539657.935313.1675
9689.005 316.5449755.356316.35259775.535312.82149810.303297.4135 9822.44 290.898
9847.018286.14989882.647 284.5169911.765286.03499938.736283.77619993.366274.6314
10007.07274.249210023.88278.154210048.78290.224410076.79291.0573 10104.8296.5758
10145.24302.016310188.24 315.18710232.91321.264510308.91326.4836 10340.3  327.21
10387.61331.589310404.24331.759810461.74337.231810474.26337.389910500.97340.7436
#Mann= 3 , 0 , 0
9499.088  0.1128       09499.088  0.1128       010500.97  0.1128       0
#XS Ineff= 2 , 0
       0                10100.16       0
Bank Sta=9499.088,10500.97
Exp/Cntr=0.3,0.1

Type RM Length L Ch R = 1 ,7703.729,235.917700,235.917700,235.917700
XS GIS Cut Line= 6
697058.457975901838418.413792903697216.786285333  838479.9566806
697322.303399496838546.755081204697409.466599481838626.070053835
697600.719400886838839.591866912697835.011394427839029.748546503
#Sta/Elev= 30
9499.101346.21049552.961342.77939569.199343.89749590.586340.85789713.058 334.961
9736.603326.5478 9773.13329.06069810.842 327.8699823.951322.64349863.589290.9544
9882.217281.65219910.616 278.6889965.876279.55319989.862272.638710002.71271.4553
10015.52272.034110041.25284.873910091.06294.7464 10149.6310.415110192.48 315.486
10251.76318.789910313.51316.878910331.93314.759310349.89319.720710409.77327.1457
 10442.8 327.45610451.09326.092310476.28313.061910493.03311.500410500.98313.1126
#Mann= 3 , 0 , 0
9499.101    0.12       09499.101    0.12       010500.98    0.12       0
#XS Ineff= 2 , 0
       0                               0
Bank Sta=9499.101,10500.98
Exp/Cntr=0.3,0.1

Type RM Length L Ch R = 1 ,7467.811,235.917800,235.917800,235.917800
XS GIS Cut Line= 6
696880.847751385838614.015173628697006.074603472838674.284606403
697124.884689182838742.128505527697184.397182619838780.939654683
697452.010298439838964.143621475 697729.78256686839143.702760509
#Sta/Elev= 30
 9499.02361.21529525.293362.66929580.931370.94169636.812373.46489648.172377.2011
9659.555376.78699670.938381.0804 9682.32 382.9079702.204383.45379741.338 377.399
 9786.93362.90879834.684340.4338 9858.85 338.5339919.902315.31459944.323297.5387
9956.534282.22689968.684273.5301 9992.65269.679410004.65  270.5910047.11280.7647
10101.33 277.02510161.76283.656910197.61279.500810209.52279.649510245.49281.5821
10269.05289.835110319.17290.1461 10352.4299.077910411.28  320.2410500.99336.0355
#Mann= 3 , 0 , 0
 9499.02    0.12       0 9499.02    0.12       010500.99    0.12       0
#XS Ineff= 2 , 0
       0                10055.61       0
Bank Sta=9499.02,10500.99
Exp/Cntr=0.3,0.1

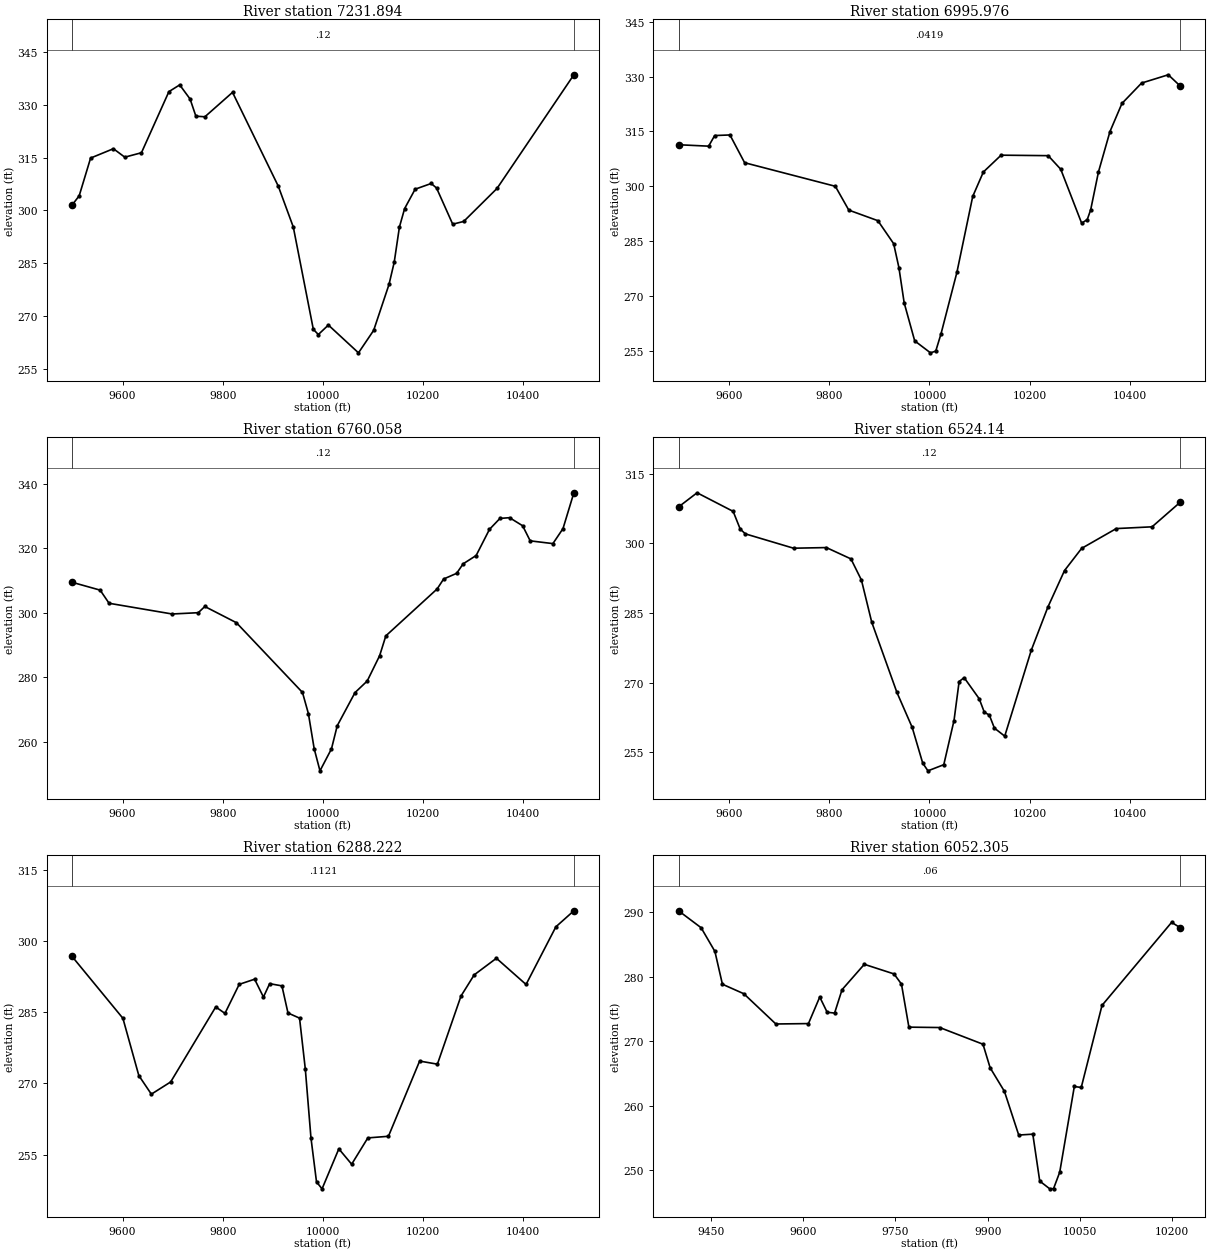
Type RM Length L Ch R = 1 ,7231.894,235.917700,235.917700,235.917700
XS GIS Cut Line= 6
696732.507573065838922.333248673697019.557464649839049.331910391
697124.729041423 839065.83662386697284.034250617839063.658543275
 697380.63562189839086.423856663697669.573128307839226.295831901
#Sta/Elev= 30
9499.139301.4825 9513.36304.12899536.127314.84679581.662317.50729604.373315.1024
 9637.65316.36369692.466 333.7319714.001 335.647 9734.77331.62689746.302326.7569
9764.319326.58459819.479 333.5289910.738306.8879 9940.79295.24489980.794266.1568
9990.795264.691410010.81267.3878 10070.9 259.48610101.24265.877810131.83278.9161
10142.24285.224210152.65295.246210163.06300.5008   10184305.997310216.06307.6209
10226.74306.344910259.04296.053110280.96296.833410347.46306.211510500.89338.5233
#Mann= 3 , 0 , 0
9499.139    0.12       09499.139    0.12       010500.89    0.12       0
#XS Ineff= 2 , 0
       0                10043.97       0
Bank Sta=9499.139,10500.89
Exp/Cntr=0.3,0.1

Type RM Length L Ch R = 1 ,6995.976,235.917800,235.917800,235.917800
XS GIS Cut Line= 6
696745.303112972839077.342258982696887.275720427839170.981772366
 696979.40982246839220.343229017697383.469782997839363.348384952
697505.720191046839422.445394184697645.489634836839505.491361391
#Sta/Elev= 30
9499.048311.36129559.142310.97199571.234313.87879601.697314.03819630.986306.4415
9812.144299.99249839.006293.47529897.067290.58299928.573284.29889939.075277.7408
9949.576 268.108 9970.58257.704110002.09254.425110012.63254.897410023.18259.6488
 10054.8276.409610086.45 297.217 10107.7 303.90310143.12308.506310237.14308.3721
10262.22304.6475 10303.9289.909210315.12290.885710321.94293.539110337.55303.9394
10360.48314.966810384.42322.658610423.64328.238110476.92330.502510500.97327.3983
#Mann= 3 , 0 , 0
9499.048  0.0419       09499.048  0.0419       010500.97  0.0419       0
#XS Ineff= 2 , 0
       0                               0
Bank Sta=9499.048,10500.97
Exp/Cntr=0.3,0.1

Type RM Length L Ch R = 1 ,6760.058,235.917700,235.917700,235.917700
XS GIS Cut Line= 6
696749.861358136839157.694789732696895.555088403839295.810124721
697034.006144088839466.665743624697162.709905574839549.089118164
697229.743630376 839598.17522127697491.233748908839822.716906253
#Sta/Elev= 30
9499.149309.46379555.191307.02519573.036302.94489698.878299.61949751.133300.0215
9764.177301.94569827.197296.9205 9959.15275.26519970.959268.70499982.519257.8069
9994.078250.932410017.06257.769110028.56264.933610064.03275.220910088.39278.8162
10113.18286.670410125.58  292.8310227.99307.395110240.97310.479110266.94312.2391
10279.93315.187810305.89317.774710332.51325.894810353.38  329.2810372.54329.5183
10398.69 327.00810413.79322.3233 10459.1321.467210479.29326.128210500.96337.2447
#Mann= 3 , 0 , 0
9499.149    0.12       09499.149    0.12       010500.96    0.12       0
#XS Ineff= 2 , 0
       0                               0
Bank Sta=9499.149,10500.96
Exp/Cntr=0.3,0.1

Type RM Length L Ch R = 1 , 6524.14,235.917800,235.917800,235.917800
XS GIS Cut Line= 6
696697.696635239839141.072473677696839.666204512839281.776865217
696908.651187424839392.110735638696925.237654816839480.198102322
696897.203832556839693.831526096697066.274627464 840012.38418212
#Sta/Elev= 30
9499.206307.87049536.238310.92689608.238306.91119622.343303.0953 9632.59302.0651
9728.762298.97129794.328299.10669843.357296.66349864.291292.09429884.786283.0313
9935.055267.8789 9965.61260.31919986.557252.6319 9997.03 250.95110028.64252.2767
10049.07261.804210059.28270.216810069.31271.049910099.35 266.50310109.47263.6149
10119.59262.9669 10129.7260.1652 10150.3258.434910203.21276.939510236.34286.2499
10269.65294.1526 10303.8298.932710372.96303.205810444.39303.5844 10500.8308.9086
#Mann= 3 , 0 , 0
9499.206    0.12       09499.206    0.12       0 10500.8    0.12       0
#XS Ineff= 2 , 0
       0                 10074.3       0
Bank Sta=9499.206,10500.8
Exp/Cntr=0.3,0.1

Type RM Length L Ch R = 1 ,6288.222,235.917700,235.917700,235.917700
XS GIS Cut Line= 6
696361.198527957839301.897728601696576.005527628839553.086385437
696652.499784905839613.247162873696764.900021455 839673.53671856
696811.220180797839714.050882958697021.979036373840035.127802588
#Sta/Elev= 30
9499.074296.72889600.558283.7069 9632.37 271.6469657.373267.7314 9695.95270.3056
9785.939286.10069804.288284.7374 9832.78290.85219863.541291.93739881.161288.1787
 9893.57290.9981 9918.07290.53039930.144284.8247 9953.24283.73869964.787272.9955
9976.027258.53539987.115249.25559998.204247.798310031.67256.2178 10057.3252.9834
10089.57258.521110130.73 258.86410192.99274.698710228.47 274.04910275.61288.3997
10301.89292.844710346.31296.345510405.47290.826610465.03302.968210500.92306.3433
#Mann= 3 , 0 , 0
9499.074  0.1121       09499.074  0.1121       010500.92  0.1121       0
#XS Ineff= 2 , 0
       0                10085.74       0
Bank Sta=9499.074,10500.92
Exp/Cntr=0.3,0.1

Type RM Length L Ch R = 1 ,6052.305,100.651800,100.651800,100.651800
XS GIS Cut Line= 6
696243.850227454839326.627664735 696343.63438063839468.343085492
696519.477920833839727.300503544696559.721961291839795.008427348
696632.581897588839935.879628255696676.539411945840017.441763125
#Sta/Elev= 30
9397.057290.24519433.793287.61249456.217283.93519468.447278.83979503.271277.3637
 9555.38272.6666 9608.41272.73039626.775276.85229638.862274.4874 9650.95274.3615
9663.037 277.987  9699.3 281.9339747.651280.43869759.738278.86099771.826272.1757
9822.021272.11469892.352269.52439903.985265.86899927.251262.20299950.517255.4218
9973.416 255.5589984.682248.2755   10001247.069310007.18247.105810017.21249.6541
10040.96262.961910052.21262.806210085.99275.551510199.28288.450510213.41287.6014
#Mann= 3 , 0 , 0
9397.057    0.06       09397.057    0.06       010213.41    0.06       0
#XS Ineff= 2 , 0
       0                               0
Bank Sta=9397.057,10213.41
Exp/Cntr=0.3,0.1

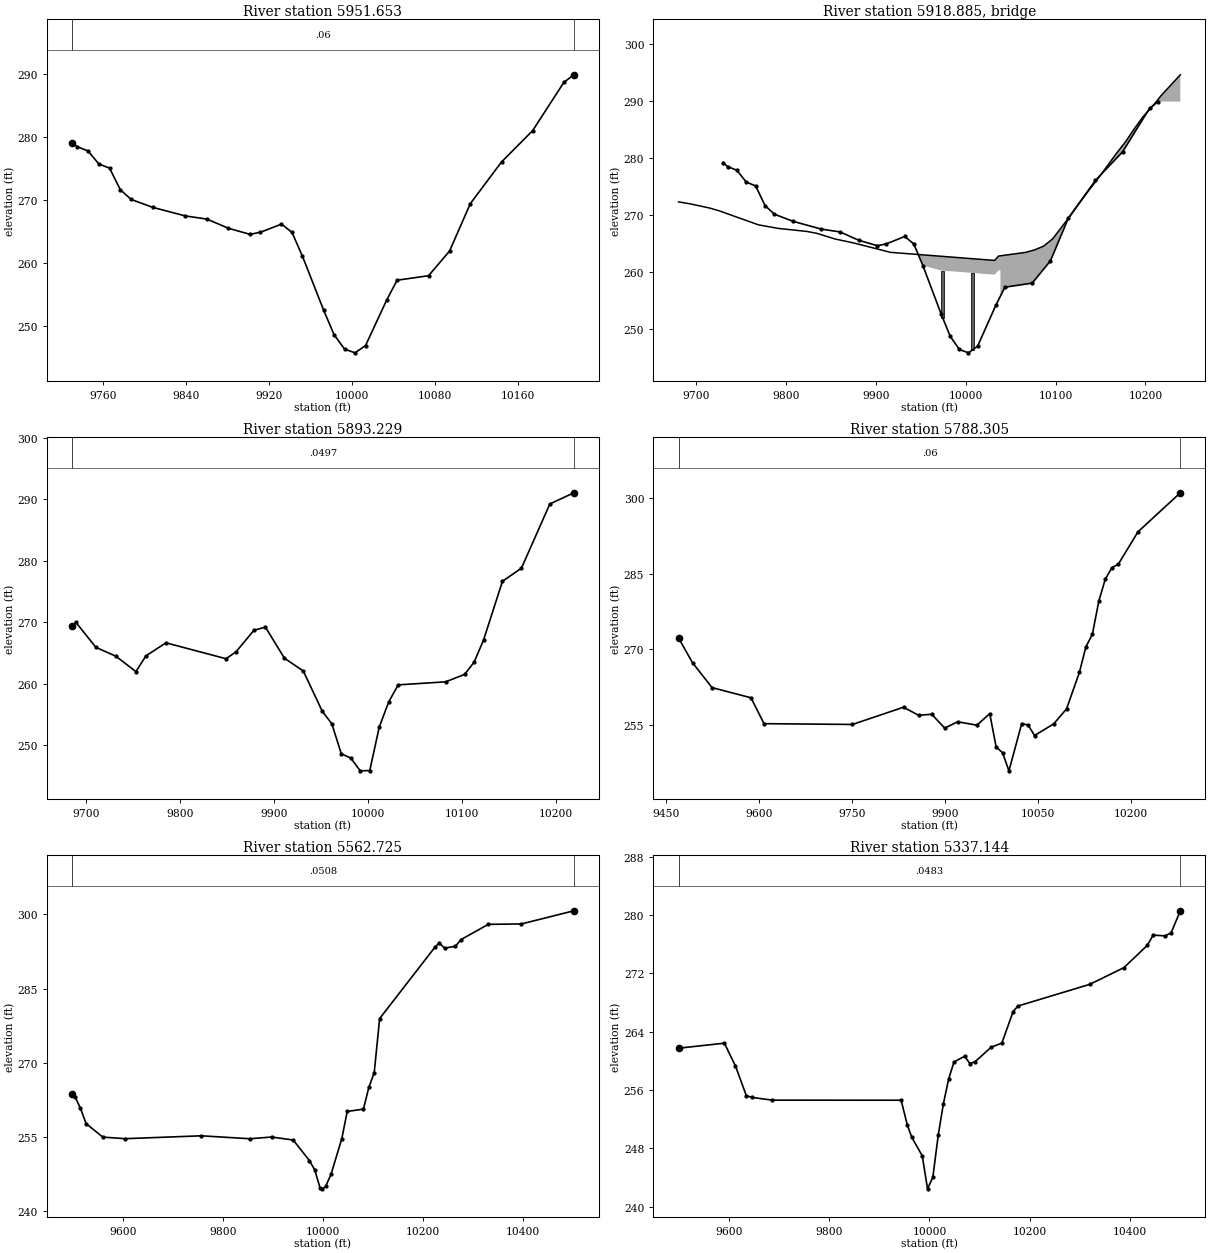
Type RM Length L Ch R = 1 ,5951.653,58.424300,58.424300,58.424300
XS GIS Cut Line= 4
696418.486971855839600.270674258696465.685605198839760.746027678
 696497.15136078839951.113848865696505.804443508 840074.61693947
#Sta/Elev= 30
9730.179279.17749735.109278.51719745.532 277.8559755.956275.78419766.379275.1103
9776.803271.66399787.226270.14369808.073268.88839839.344267.53469860.191267.0295
9881.038265.57239901.763264.61089911.899264.9399 9932.17266.23049942.306264.9243
9952.441261.11999972.713252.62199982.848248.69989992.984246.389610003.12245.7984
10013.26246.958410033.53254.132210043.66257.324610074.07258.0431 10094.3261.9501
10114.35269.488810144.42276.096210174.49281.076110204.57288.733110214.21 289.937
#Mann= 3 , 0 , 0
9730.179    0.06       09730.179    0.06       010214.21    0.06       0
#XS Ineff= 2 , 0
       0                10036.71       0
Bank Sta=9730.179,10214.21
Exp/Cntr=0.3,0.1

Type RM Length L Ch R = 3 ,5918.885,,,
BEGIN DESCRIPTION:
END DESCRIPTION:
Bridge Culvert--1,0,-1,-1, 0
Deck Dist Width WeirC Skew NumUp NumDn MinLoCord MaxHiCord MaxSubmerge Is_Ogee
14.122150,30.180000,2.6,0, 32, 32, , , 0.95, 0, 0,0,,
 9680.60 9694.05 9715.59 9726.36 9769.45 9790.99 9823.30 9834.07 9854.78 9875.06
 9910.42 9910.42 9916.0110032.2910036.4710038.7010038.7010066.6510076.7210086.78
10096.8410116.9710127.0310137.0910147.1510167.2810177.3410187.4010197.4710207.53
10217.5910238.81
  272.31  271.95  271.21  270.71  268.28  267.66  267.12  266.80  265.79  265.11
  263.69  263.69  263.45  262.03  262.78  262.84  262.84  263.44  263.88  264.54
  265.83  269.98  272.20  274.34  276.38  280.73  282.75  285.10  287.29  289.03
  291.00  294.63
 -727.69 -728.05 -728.79 -729.29 -731.72 -732.34 -732.88 -733.20 -734.21 -734.89
 -736.31  261.19  260.95  259.53  260.28  260.34 -737.16 -736.56 -736.12 -735.46
 -734.17 -730.02 -727.80 -725.66 -723.62 -719.27 -717.25 -714.90 -712.71 -710.97
 -709.00 -705.37
 9680.60 9694.05 9715.59 9726.36 9769.45 9790.99 9823.30 9834.07 9854.78 9875.06
 9910.76 9910.76 9916.0110032.2910036.4710039.0410039.0410066.6510076.7210086.78
10096.8410116.9710127.0310137.0910147.1510167.2810177.3410187.4010197.4710207.53
10217.5910238.81
  272.31  271.95  271.21  270.71  268.28  267.66  267.12  266.80  265.79  265.11
  263.67  263.67  263.45  262.03  262.78  262.85  262.85  263.44  263.88  264.54
  265.83  269.98  272.20  274.34  276.38  280.73  282.75  285.10  287.29  289.03
  291.00  294.63
 -727.69 -728.05 -728.79 -729.29 -731.72 -732.34 -732.88 -733.20 -734.21 -734.89
 -736.33  261.17  260.95  259.53  260.28  260.35 -737.15 -736.56 -736.12 -735.46
 -734.17 -730.02 -727.80 -725.66 -723.62 -719.27 -717.25 -714.90 -712.71 -710.97
 -709.00 -705.37
Pier Skew, UpSta & Num, DnSta & Num=  ,9941.74, 2 ,9942.08, 2 , 0 , 0 , 0 ,,
    3.00    3.00
 -736.87  263.13
    3.00    3.00
 -736.87  263.13
Pier Skew, UpSta & Num, DnSta & Num=  ,9974.56, 2 ,9974.90, 2 , 0 , 0 , 0 ,,
    3.00    3.00
 -737.27  262.73
    3.00    3.00
 -737.27  262.73
Pier Skew, UpSta & Num, DnSta & Num=  ,10007.38, 2 ,10007.72, 2 , 0 , 0 , 0 ,,
    3.00    3.00
 -737.67  262.33
    3.00    3.00
 -737.67  262.33
BR Coef=-1 , 0 , 0 ,, 0 ,,,0.8,0,1,0,
WSPro=,,,, 1 ,,,, 0 ,,,, 0 ,,,,-1 ,-1 ,-1 , 0 , 0 , 0 , 0 , 0
BC Design=,, 0 ,, 0 ,,,,,,

Type RM Length L Ch R = 1 ,5893.229,104.923900,104.923900,104.923900
XS GIS Cut Line= 4
696342.969158471839571.164850384696409.047245145839752.879588783
696431.073274106839918.074805528696452.312659055840090.349817246
#Sta/Elev= 30
9685.373269.35769689.454269.96649710.735265.89649732.017264.45429753.298261.9532
9763.938264.5126 9785.22266.63519849.064264.05029859.704265.16629878.729268.6747
9890.957 269.1939911.134264.14189931.311262.04129951.488255.48999961.576253.4825
9971.665248.59389981.753247.89859991.842245.819610001.93245.868510012.02252.9319
10022.11257.0372 10032.2259.802510082.59260.290810102.74261.499210112.82263.4753
10122.89267.067910143.05276.6428 10163.2278.770210193.42289.211810218.97 291.033
#Mann= 3 , 0 , 0
9685.373  0.0497       09685.373  0.0497       010218.97  0.0497       0
#XS Ineff= 2 , 0
       0                10040.74       0
Bank Sta=9685.373,10218.97
Exp/Cntr=0.3,0.1

Type RM Length L Ch R = 1 ,5788.305,225.580300,225.580300,225.580300
XS GIS Cut Line= 6
696146.179357976839393.429473653696195.697238326839551.797324792
 696245.17241472 839655.62079069696279.394746482839743.101903901
696365.820165813840053.601118535696403.238725662840159.136302009
#Sta/Elev= 30
9470.243272.25679492.843 267.3249524.275262.3819 9587.14260.35499608.095255.2098
 9750.78255.05339833.054258.47999857.577 256.8659878.522257.08459899.466254.3357
 9920.41255.58399951.484254.91279972.137257.20949982.464250.5632 9992.79249.4359
10003.11245.828810023.74255.242110034.05254.924410044.37 252.85610075.31255.1713
10096.02258.150710116.86265.462610127.28270.5011 10137.7272.993810148.12279.6413
10158.54283.962310168.98286.195310179.56286.9384 10211.3293.3711 10279.5301.1262
#Mann= 3 , 0 , 0
9470.243    0.06       09470.243    0.06       0 10279.5    0.06       0
#XS Ineff= 2 , 0
       0  9913.4        10053.86       0
Bank Sta=9470.243,10279.5
Exp/Cntr=0.3,0.1

Type RM Length L Ch R = 1 ,5562.725,225.580300,225.580300,225.580300
XS GIS Cut Line= 6
 695913.18763205839509.924941826695957.693232664839600.386061671
695997.942732781839691.124158464696224.317649464840247.049462893
696264.509645381840333.781059795696313.463641995840427.830439448
#Sta/Elev= 30
 9499.02263.73149504.676263.20239515.821260.83719526.966257.7421  9560.4 255.016
9604.884 254.6969757.206255.27739854.271254.68219897.411255.0347 9940.55254.4255
9972.905 250.287 9983.69248.36219994.475244.6597    9999244.566310005.27245.0547
10016.06247.480410037.64254.721710048.43260.1962 10080.8260.667110091.59265.0619
10102.38268.057310113.17278.956410223.94293.415910232.01294.225410242.87293.1804
10264.57293.551410275.43294.893810330.16297.986910396.32298.065310500.98300.7237
#Mann= 3 , 0 , 0
 9499.02  0.0508       0 9499.02  0.0508       010500.98  0.0508       0
#XS Ineff= 2 , 0
       09802.507                       0
Bank Sta=9499.02,10500.98
Exp/Cntr=0.3,0.1

Type RM Length L Ch R = 1 ,5337.144,225.580300,225.580300,225.580300
XS GIS Cut Line= 6
695716.889370873839582.678739038695811.866349307839793.072974616
695933.874211743840148.862147254 695977.47896526840260.854429991
696038.856201062840383.901856991696111.089241276840500.402246815
#Sta/Elev= 30
9499.034261.74849590.564262.43929612.695259.30739634.395255.23889645.245255.0026
9686.492254.62179943.487254.61269955.629 251.2659964.539249.55229985.662246.9872
9996.231242.456210006.81244.043410017.69249.871510027.97254.162710038.55257.5747
10049.13259.866910070.29260.644410080.87259.634110091.45259.916110123.32261.8868
10144.64262.449510167.08266.773510176.71267.534710319.77270.498110388.42 272.802
10434.96275.858910446.77277.263410470.65277.155210482.58277.580810500.97280.6009
#Mann= 3 , 0 , 0
9499.034  0.0483       09499.034  0.0483       010500.97  0.0483       0
#XS Ineff= 2 , 0
       0 9714.48                       0
Bank Sta=9499.034,10500.97
Exp/Cntr=0.3,0.1