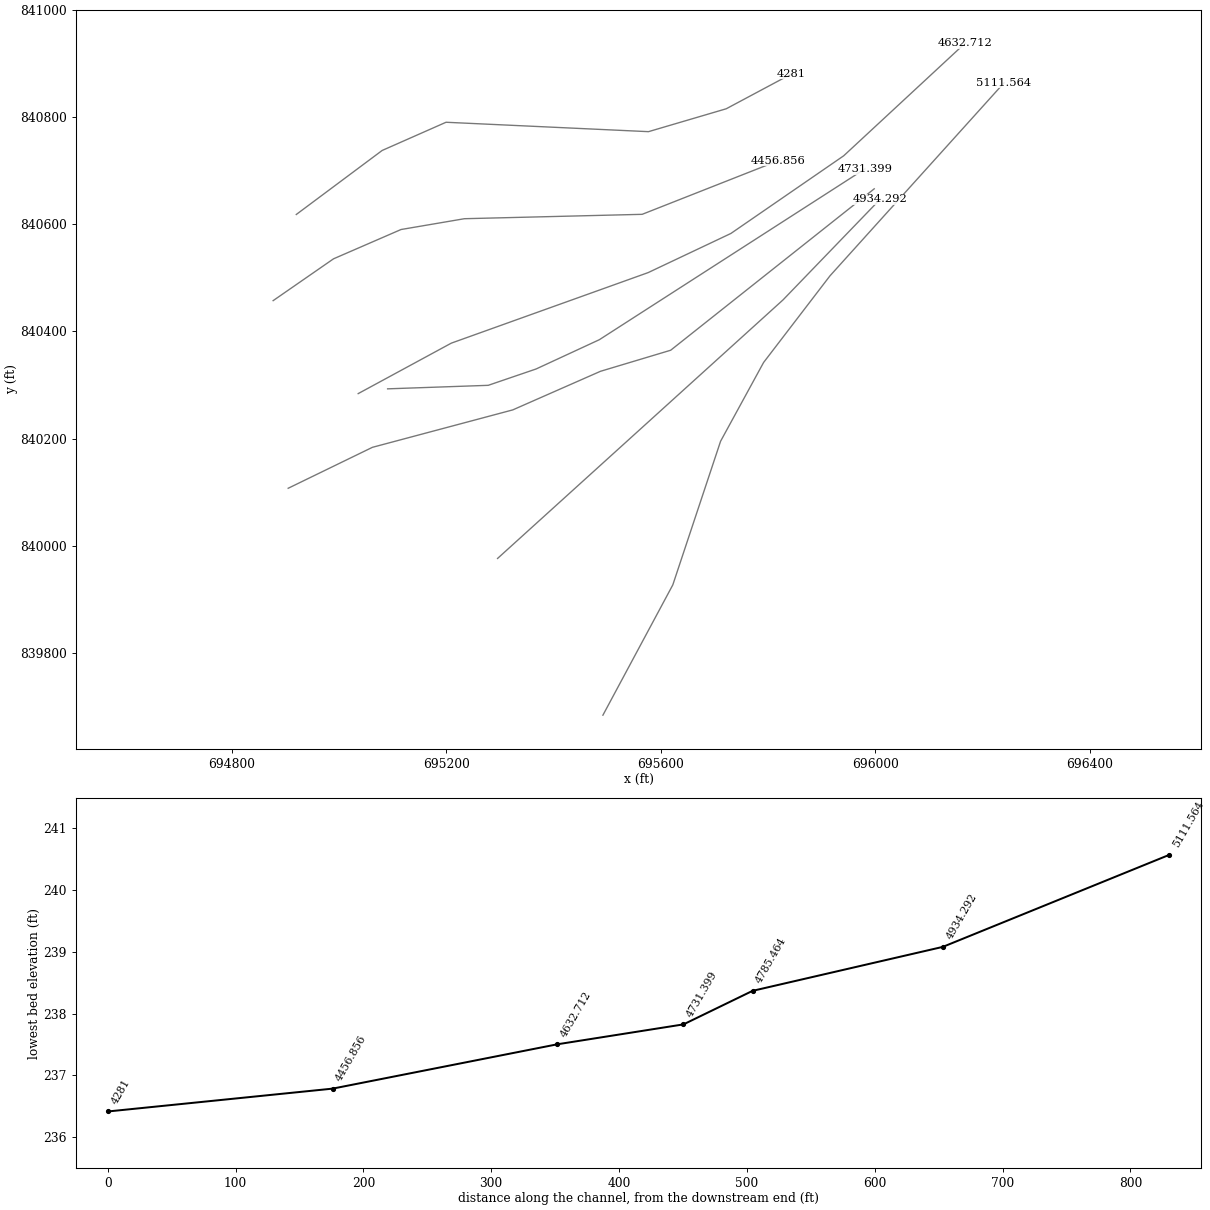
HEC-RAS study 13386_ras.prj: 13386

--- 13386_ras.g01 (geometry) --- (continued)

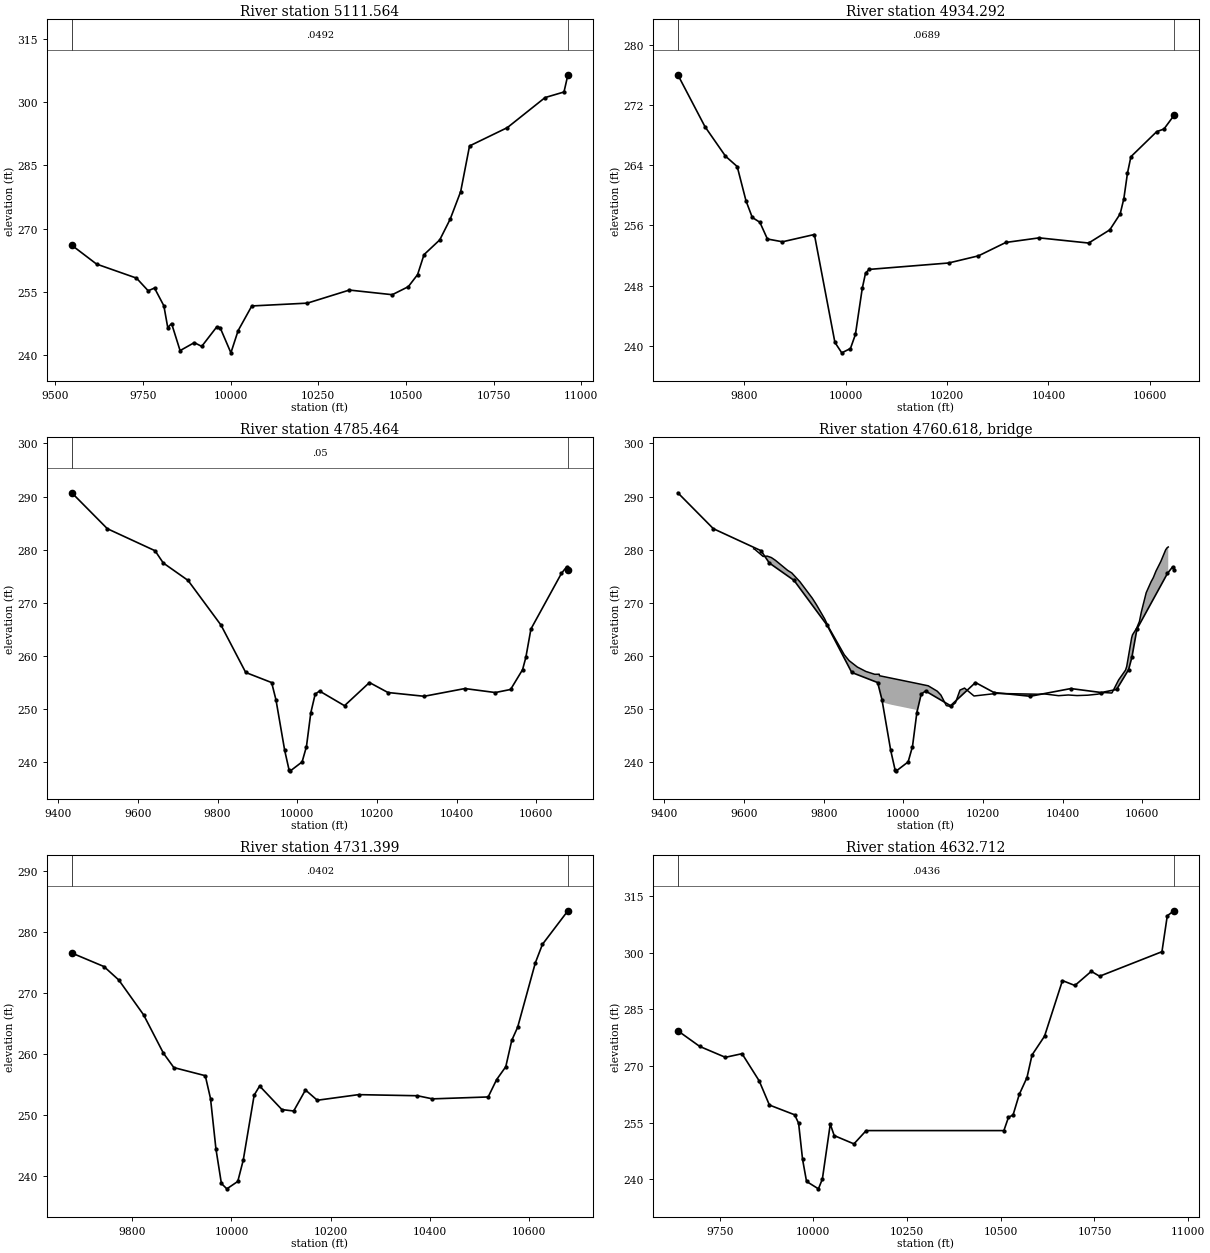
Type RM Length L Ch R = 1 ,5111.564,177.271800,177.271800,177.271800
XS GIS Cut Line= 6
695491.747353068839684.036318193695622.077377621839926.981705096
695711.191604079840194.905002916695791.381038396840341.776294627
695915.214514291840503.407187901696239.800506743840863.317414007
#Sta/Elev= 30
9547.221 266.0519617.788261.59459731.691258.27159765.103255.2622 9783.09255.9227
9809.813251.70389820.873246.54939831.781247.51859856.032241.0993 9896.52242.9896
9917.705242.10529959.925246.64379970.188246.541510000.96240.573210021.52245.8307
10060.57251.6761   10219252.343310338.76 255.43810461.08254.3405 10506.8256.2375
10533.27259.097210551.59 263.82410596.39 267.31210626.25272.235110656.11278.7466
10681.39289.563910789.12293.899610896.85301.023110950.71302.339710961.91306.4159
#Mann= 3 , 0 , 0
9547.221  0.0492       09547.221  0.0492       010961.91  0.0492       0
#XS Ineff= 2 , 0
       09876.812        10158.93       0
Bank Sta=9547.221,10961.91
Exp/Cntr=0.3,0.1

Type RM Length L Ch R = 1 ,4934.292,148.828100,148.828100,148.828100
XS GIS Cut Line= 3
695295.253895313839976.328407675695827.570570856840458.467691645
696008.645505548840646.087503538
#Sta/Elev= 30
9668.824 275.988 9722.45269.09839762.926265.18399786.015263.80929803.402259.2522
9815.807257.04759830.704256.4157  9845.6254.19179875.392253.82189938.323254.7884
9978.799240.47149992.291239.082310009.46239.654110019.28241.522410032.77247.6372
10039.25249.662310046.26250.155610203.11251.006710262.13251.9577 10316.1253.7336
10381.86 254.34310479.49253.654710521.19255.405410541.73257.528710548.98259.5649
10556.13262.949510562.88265.114310613.73 268.43910628.13268.791210647.78270.5856
#Mann= 3 , 0 , 0
9668.824  0.0689       09668.824  0.0689       010647.78  0.0689       0
#XS Ineff= 2 , 0
       09927.011        10136.64       0
Bank Sta=9668.824,10647.78
Exp/Cntr=0.3,0.1

Type RM Length L Ch R = 1 ,4785.464,54.065300,54.065300,54.065300
XS GIS Cut Line= 6
 694904.74289149840107.225950822695061.819943309840183.582851022
695323.615029633840253.394874036695487.236958593840325.388522774
695618.134501785840364.657785714695997.737376958840665.722134992
#Sta/Elev= 30
9433.896 290.7149523.134283.95259642.889279.80539663.588277.49569725.684274.2206
 9808.48265.80289870.577256.88639935.632254.98589946.557 251.7179968.407242.2091
9979.333238.55529982.798238.370510012.11240.050910023.03242.944810033.96249.3009
10044.88252.799410055.81253.395510118.56250.6307 10181.2254.993610227.65253.1143
10318.55252.406510420.65253.860210497.23253.110210535.52253.6884 10565.6257.4186
10573.81259.729110586.58265.069410663.15275.536310675.92276.751310679.41276.2562
#Mann= 3 , 0 , 0
9433.896    0.05       09433.896    0.05       010679.41    0.05       0
#XS Ineff= 2 , 0
       09930.242        10045.81       0
Bank Sta=9433.896,10679.41
Exp/Cntr=0.3,0.1

Type RM Length L Ch R = 3 ,4760.618,,,
BEGIN DESCRIPTION:
END DESCRIPTION:
Bridge Culvert--1,0,-1,-1, 0
Deck Dist Width WeirC Skew NumUp NumDn MinLoCord MaxHiCord MaxSubmerge Is_Ogee
9.807650,34.450000,2.6,0, 60, 60, , , 0.95, 0, 0,0,,
 9624.25 9627.52 9648.09 9658.37 9668.66 9678.94 9709.79 9720.07 9740.64 9771.49
 9781.77 9802.34 9812.62 9851.90 9864.04 9884.60 9906.00 9928.36 9939.54 9940.20
 9947.59 9947.5910032.5610032.5610062.5210085.2610094.3710108.0710119.4810130.88
10142.2910153.7010177.5110233.5410340.9010353.1210389.7910414.2310436.1910463.12
10487.5710505.7610523.1610524.2310540.5510557.9410560.9010573.1210575.3310585.34
10592.7310597.5710609.7910622.0110627.5110634.2310646.4510658.6810662.3010665.13
  280.17  280.05  278.73  278.79  278.52  278.00  276.10  275.62  273.95  270.87
  269.66  267.01  265.40  260.21  259.11  257.91  257.08  256.54  256.56  256.27
  256.16  256.16  254.85  254.85  254.38  253.36  252.64  250.65  250.48  251.17
  253.57  253.95  252.46  252.94  252.79  252.86  252.52  252.65  252.54  252.61
  252.80  253.10  253.02  253.09  255.48  257.34  258.04  263.36  263.97  265.15
  266.48  268.27  271.91  273.96  274.72  275.96  277.78  279.98  280.36  280.51
 -719.83 -719.95 -721.27 -721.21 -721.48 -722.00 -723.90 -724.38 -726.05 -729.13
 -730.34 -732.99 -734.60 -739.79 -740.89 -742.09 -742.92 -743.46 -743.44 -743.73
 -743.84  251.16  249.85 -745.15 -745.62 -746.64 -747.36 -749.35 -749.52 -748.83
 -746.43 -746.05 -747.54 -747.06 -747.21 -747.14 -747.48 -747.35 -747.46 -747.39
 -747.20 -746.90 -746.98 -746.91 -744.52 -742.66 -741.96 -736.64 -736.03 -734.85
 -733.52 -731.73 -728.09 -726.04 -725.28 -724.04 -722.22 -720.02 -719.64 -719.49
 9624.25 9627.52 9648.09 9658.37 9668.66 9678.94 9709.79 9720.07 9740.64 9771.49
 9781.77 9802.34 9812.62 9851.90 9864.04 9884.60 9906.00 9928.36 9939.54 9940.20
 9956.51 9956.5110041.4810041.4810062.5210085.2610094.3710108.0710119.4810130.88
10142.2910153.7010177.5110233.5410340.9010353.1210389.7910414.2310436.1910463.12
10487.5710505.7610523.1610524.2310540.5510557.9410560.9010573.1210575.3310585.34
10592.7310597.5710609.7910622.0110627.5110634.2310646.4510658.6810662.3010665.13
  280.17  280.05  278.73  278.79  278.52  278.00  276.10  275.62  273.95  270.87
  269.66  267.01  265.40  260.21  259.11  257.91  257.08  256.54  256.56  256.27
  256.02  256.02  254.71  254.71  254.38  253.36  252.64  250.65  250.48  251.17
  253.57  253.95  252.46  252.94  252.79  252.86  252.52  252.65  252.54  252.61
  252.80  253.10  253.02  253.09  255.48  257.34  258.04  263.36  263.97  265.15
  266.48  268.27  271.91  273.96  274.72  275.96  277.78  279.98  280.36  280.51
 -719.83 -719.95 -721.27 -721.21 -721.48 -722.00 -723.90 -724.38 -726.05 -729.13
 -730.34 -732.99 -734.60 -739.79 -740.89 -742.09 -742.92 -743.46 -743.44 -743.73
 -743.98  251.02  249.71 -745.29 -745.62 -746.64 -747.36 -749.35 -749.52 -748.83
 -746.43 -746.05 -747.54 -747.06 -747.21 -747.14 -747.48 -747.35 -747.46 -747.39
 -747.20 -746.90 -746.98 -746.91 -744.52 -742.66 -741.96 -736.64 -736.03 -734.85
 -733.52 -731.73 -728.09 -726.04 -725.28 -724.04 -722.22 -720.02 -719.64 -719.49
BR Coef=-1 , 0 , 0 ,, 0 ,,,0.8,0,1,0,
WSPro=,,,, 1 ,,,, 0 ,,,, 0 ,,,,-1 ,-1 ,-1 , 0 , 0 , 0 , 0 , 0
BC Design=,, 0 ,, 0 ,,,,,,

Type RM Length L Ch R = 1 ,4731.399,98.686400,98.686400,98.686400
XS GIS Cut Line= 5
695090.181077629840292.664136976695277.800889552840299.209014148
 695367.24754402840329.751774207695485.055332869840384.292417198
695980.284371167840702.809772223
#Sta/Elev= 30
9677.964276.47769742.822274.2633 9772.84272.05069822.871266.34319862.895260.0527
9883.872257.70049947.273 256.371 9957.84252.62529968.758244.38189979.778238.7062
9990.798237.827510012.84239.041810023.86242.5303 10045.9253.188110056.92254.6797
10101.86250.817510125.64250.584310149.42254.0318 10173.2252.347110256.43253.2667
10375.32253.085910405.61252.5744   10518252.887310535.01255.7291 10553.5257.8451
10565.56262.166210577.45264.314510613.12274.867610627.44277.898510678.85 283.402
#Mann= 3 , 0 , 0
9677.964  0.0402       09677.964  0.0402       010678.85  0.0402       0
#XS Ineff= 2 , 0
       09943.872        10053.71       0
Bank Sta=9677.964,10678.85
Exp/Cntr=0.3,0.1

Type RM Length L Ch R = 1 ,4632.712,175.856200,175.856200,175.856200
XS GIS Cut Line= 6
695035.323625684840283.764130189695208.989259305840377.905227821
695576.197908485840509.484901783695730.421285915840582.465260048
695940.852551243840727.337852137696167.467236075840937.461083556
#Sta/Elev= 30
9638.355 279.326 9696.86275.17659765.261272.29849809.694273.25699855.469266.0683
9882.716259.67319950.034257.09639960.621254.86129971.209245.29939981.796239.4628
 10013.5237.505210024.03240.090610045.09254.624810055.62251.593310108.26249.3966
10140.91252.914610508.31252.9132 10520.5256.419310532.86257.0676 10549.4262.5034
10569.93266.949410583.45 272.92310616.78277.891110664.58292.596910697.74291.2969
10741.49295.043710763.68293.747310930.01300.235510944.25309.741210961.99311.0632
#Mann= 3 , 0 , 0
9638.355  0.0436       09638.355  0.0436       010961.99  0.0436       0
#XS Ineff= 2 , 0
       09940.494        10047.12       0
Bank Sta=9638.355,10961.99
Exp/Cntr=0.3,0.1

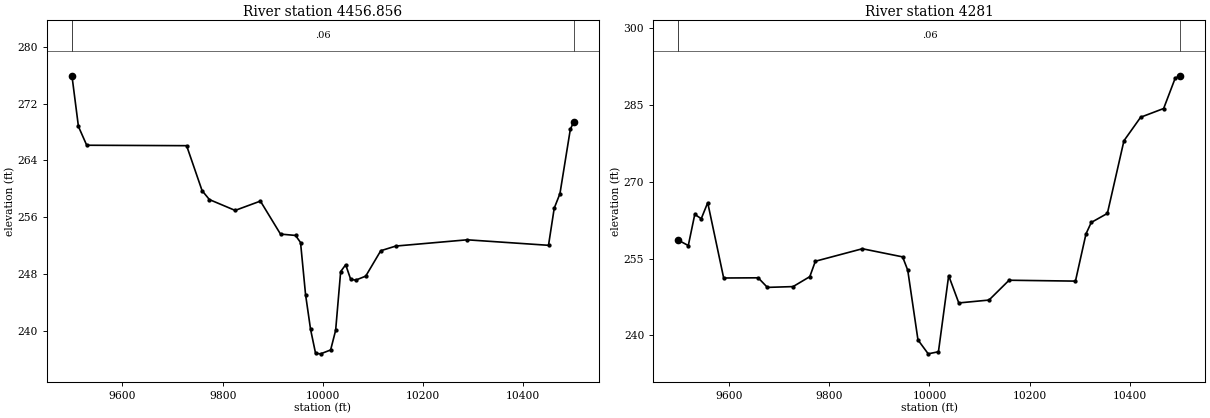
Type RM Length L Ch R = 1 ,4456.856,175.856100,175.856100,175.856100
XS GIS Cut Line= 6
694876.714141743840457.173312241694989.318709121840535.167285874
695115.220015545840589.814409914695233.474134261840609.968580506
695564.936145081840618.136223458695819.248684402 840718.33808938
#Sta/Elev= 30
9499.141275.91859512.084268.78529528.621266.14299728.023266.08149758.892259.7566
9773.522258.49689824.871256.97159875.306258.28259915.435253.63829945.441253.4506
9955.443252.45369965.451245.12299975.459240.23149985.467236.84589995.475236.7871
 10015.5237.334210025.51240.099810035.52248.359310045.53249.325210055.54247.2744
10065.54247.160810085.54247.720410115.56251.296710145.61251.9556   10288252.8353
10450.42252.060210461.83257.288610473.23259.329710493.94268.375510500.88269.4539
#Mann= 3 , 0 , 0
9499.141    0.06       09499.141    0.06       010500.88    0.06       0
#XS Ineff= 2 , 0
       0                 10042.7       0
Bank Sta=9499.141,10500.88
Exp/Cntr=0.3,0.1

Type RM Length L Ch R = 1 ,    4281,0.000000,0.000000,0.000000
XS GIS Cut Line= 6
694919.839653152840617.839436996 695080.03392538840737.265636825
695199.141841873840789.852006013695576.706668135840772.321331662
695721.729157173840815.000067819695843.675481289840880.106959801
#Sta/Elev= 30
9499.193258.6019 9518.79257.56459531.717263.65779544.644262.8138 9557.57265.9383
9589.397251.22899658.286251.26739676.684249.39699727.912249.54999761.289251.4928
9772.415254.50229866.218256.94359946.567255.35499956.778252.7553  9977.2 239.136
9997.622236.417210018.05236.825110038.47251.687910058.67246.359610118.97246.9217
10159.03250.793710291.52 250.62210312.57259.853310323.09262.079910355.22263.8441
10388.32278.039910421.63282.628710467.54284.332310490.76290.300210500.83290.7271
#Mann= 3 , 0 , 0
9499.193    0.06       09499.193    0.06       010500.83    0.06       0
#XS Ineff= 2 , 0
       0                10041.53       0
Bank Sta=9499.193,10500.83
Exp/Cntr=0.3,0.1